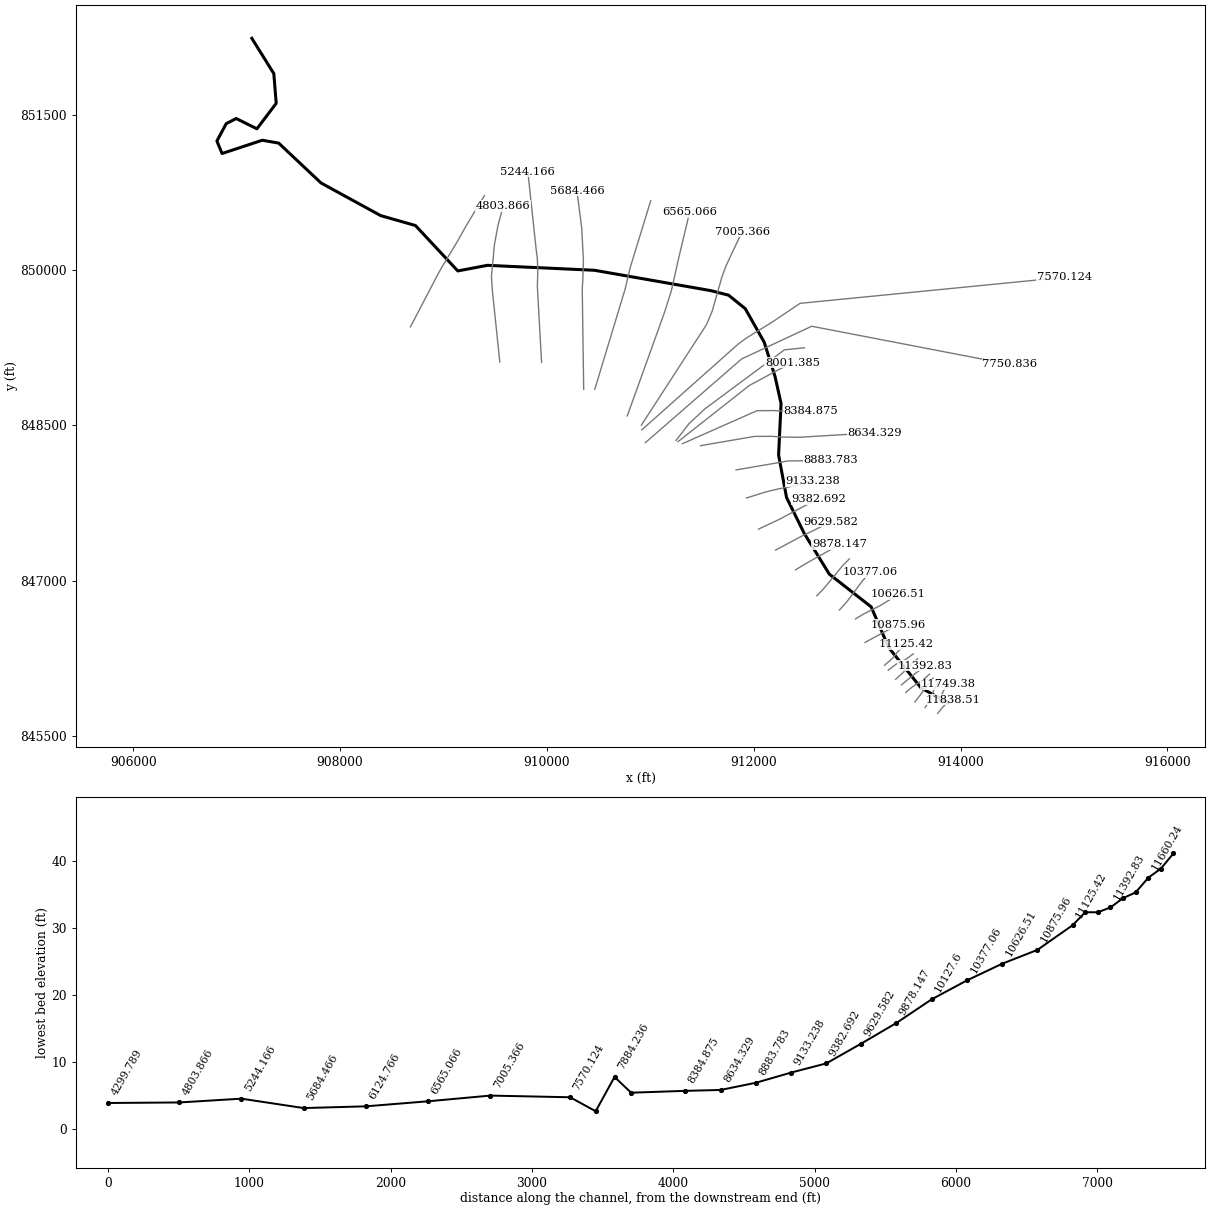
--- 16749_ras.prj (project) ---

Proj Title=16749
Current Plan=p01
Default Exp/Contr=0.3,0.1
English Units
Geom File=g01
Flow File=f01
Plan File=p01
Y Axis Title=Elevation
X Axis Title(PF)=Main Channel Distance
X Axis Title(XS)=Station
BEGIN DESCRIPTION:
RFD model 16749 exported to HEC-RAS
END DESCRIPTION:

--- 16749_ras.p01 (plan) ---

Plan Title=Plan 01
Program Version=4.10
Short Identifier=Plan 01
Geom File=g01
Flow File=f01
Subcritical Flow
Calc Critical at every XS
Secant Critical Depth

--- 16749_ras.f01 (steady flow) ---

Flow Title=Flow 01
Program Version=5.01
Number of Profiles= 6
Profile Names=10yr,25yr,50yr,100yr,100plus,500yr
River Rch & RM=16749,31,11838.51
  127.71  212.01   293.1  370.69  541.21  1017.3
River Rch & RM=16749,31,10875.96
  165.41  275.03  380.71  481.86  703.51 1276.06
River Rch & RM=16749,31,10626.51
  173.22  288.08  398.85  504.87  737.11 1328.45
River Rch & RM=16749,31,10377.06
  227.95  379.62  526.17  666.42  972.98 1687.78
River Rch & RM=16749,31, 10127.6
  229.85   382.8   530.6  672.05  981.19  1700.1
River Rch & RM=16749,31,9878.147
  237.08  394.93  547.51  693.54 1012.56 1747.04
River Rch & RM=16749,31,9629.582
  241.46  402.27  557.74  706.55 1031.57 1775.36
River Rch & RM=16749,31,9382.692
  264.92  441.65  612.66  776.37 1133.49 1926.18
River Rch & RM=16749,31,9133.238
  274.02  456.95  634.01  803.53 1173.15 1984.44
River Rch & RM=16749,31,8883.783
  277.91  463.49  643.16  815.19 1190.18 2009.47
River Rch & RM=16749,31,8634.329
  291.95  487.38  676.77  858.27 1253.07 2102.77
River Rch & RM=16749,31,8384.875
  295.94  494.17  686.32   870.5 1270.93 2129.12
River Rch & RM=16749,31,8001.385
  363.13  608.17  846.44 1075.32 1569.96 2561.39
River Rch & RM=16749,31,7884.236
  370.17  620.17  863.34 1096.99  1601.6 2606.64
River Rch & RM=16749,31,7750.836
  379.84  636.66  886.57  1126.8 1645.13  2668.8
River Rch & RM=16749,31,7570.124
   386.7   648.4  903.15 1148.12 1676.25 2713.34
River Rch & RM=16749,31,7005.366
  401.85  674.48  940.14 1195.82 1745.89 2813.36
River Rch & RM=16749,31,6565.066
  414.65  696.49  971.32 1236.01 1804.57 2897.04
River Rch & RM=16749,31,6124.766
  464.07  780.63 1089.79 1387.84 2026.24 3205.24
River Rch & RM=16749,31,5684.466
  473.68  797.19 1113.31 1418.19 2070.56 3267.37
River Rch & RM=16749,31,5244.166
  498.02  838.86 1172.19  1493.9  2181.1 3419.95
River Rch & RM=16749,31,4803.866
  509.51  858.63 1200.22 1530.04 2233.86 3492.92
River Rch & RM=16749,31,4299.789
  511.46  861.98 1204.98 1536.17 2242.81 3505.28
Boundary for River Rch & Prof#=16749,31,1
Up Type= 0
Dn Type= 2
Boundary for River Rch & Prof#=16749,31,2
Up Type= 0
Dn Type= 2
Boundary for River Rch & Prof#=16749,31,2
Up Type= 0
Dn Type= 2
Boundary for River Rch & Prof#=16749,31,2
Up Type= 0
Dn Type= 2
Boundary for River Rch & Prof#=16749,31,2
Up Type= 0
Dn Type= 2
Boundary for River Rch & Prof#=16749,31,2
Up Type= 0
Dn Type= 2

--- 16749_ras.g01 (geometry) ---

Geom Title=16749
Program Version=4.10

River Reach=16749,31
Reach XY= 30
913878.358277847845818.738149893913617.161461009845962.478702712
913303.307242106846354.433009906913135.107902265846746.168619115
912730.215965449847062.872928042912487.557205738847456.758875523
912316.859030161847803.385199065912239.813481683848214.025757391
912263.680259653848713.074069591912205.177725409848974.832278599
912100.454860456849305.798301066911917.221125983849630.006606609
  911755.7057995 849760.14643293911584.078174178849804.060586383
910459.483803076850000.852423779909423.405507316850048.671035503
909137.846554965849994.469133335908728.711615642850433.310285436
908391.813685791850529.715970385907815.746926881850844.845727333
 907406.28867736851230.264271421907247.538093937851258.305828803
906858.657326028851129.803948276906808.734929552851250.428599251
906898.721610276851418.705271603906995.357667101851468.234604477
907195.595321045851368.682847593907382.102952355851615.158532683
907358.952165206851902.679254076907146.483763234852243.512642977

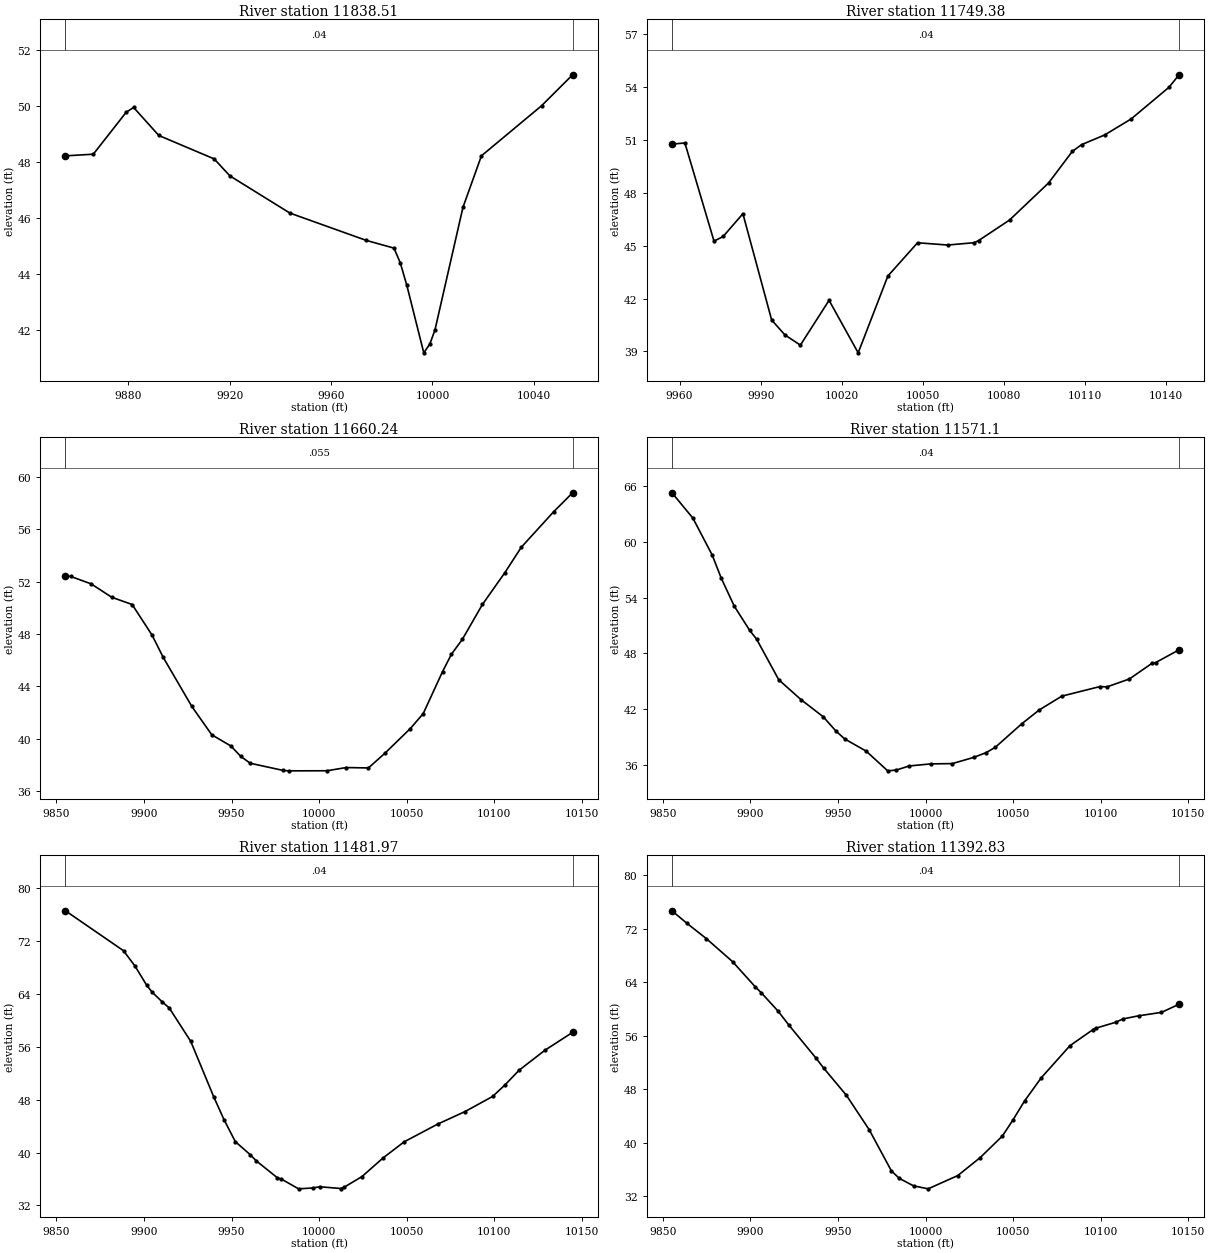
Type RM Length L Ch R = 1 ,11838.51,89.136700,89.136700,89.136700
XS GIS Cut Line= 6
 913778.08408579845716.382483707913818.914951775845766.814984581
 913845.06563875845794.983908331913866.870542847845813.739484934
 913888.48168531845824.763663806913925.315582549845848.302392475
#Sta/Elev= 19
 9855.2248.217629866.21148.277339879.17449.771699882.103 49.94429892.04148.94539
9913.88748.109469920.10947.503049943.75146.177939973.90545.20281 9984.8444.92757
9987.30744.406769989.91443.597779996.59541.19292    999941.51157   1000142.00615
10012.0446.3778610019.3448.2187110043.0750.0049210055.3251.10927
#Mann= 3 , 0 , 0
 9855.22    0.04       0 9855.22    0.04       010055.32    0.04       0
#XS Ineff= 2 , 0
       0                               0
Bank Sta=9855.22,10055.32
Exp/Cntr=0.3,0.1

Type RM Length L Ch R = 1 ,11749.38,89.136700,89.136700,89.136700
XS GIS Cut Line= 6
913791.871580178845830.557644301913798.946488033845848.137877531
913814.435946446845891.091577179913828.159042419845921.249955296
913848.356079353845957.628702547913874.672635529845998.131463688
#Sta/Elev= 23
 9957.1850.767629961.96950.833359972.74845.25834 9976.1345.524539983.43646.81674
9994.08140.77939    999939.93309 10004.739.3545110015.3241.8987410026.0938.91736
10037.0743.2774410048.0645.1671310059.2245.0384610069.0245.1712710070.6545.29185
10082.0946.4569410096.5448.5619110105.3350.3554910108.7350.7356710117.2551.28534
10127.08 52.1949 10141.153.9960110144.8454.70512
#Mann= 3 , 0 , 0
 9957.18    0.04       0 9957.18    0.04       010144.84    0.04       0
#XS Ineff= 2 , 0
       0                10041.68       0
Bank Sta=9957.18,10144.84
Exp/Cntr=0.3,0.1

Type RM Length L Ch R = 1 ,11660.24,89.136600,89.136600,89.136600
XS GIS Cut Line= 6
913656.644363781845772.529558783913677.045270699 845805.74394614
913698.668115662845845.973698552913753.611804856845967.047793739
913769.898101601845996.111541028913790.803378781846028.736769692
#Sta/Elev= 28
9855.15652.462719858.05552.401499869.79151.829659881.52650.809759893.26250.25153
9904.64347.910529910.93746.229969927.34942.467949938.70240.310779949.70439.44634
9955.248 38.66419960.66938.135039979.63437.583729982.59737.5554610004.4837.56081
10015.4937.80612 10028.237.77699 10037.5 38.883510052.15 40.784410059.5141.92597
10070.5245.1221910075.6146.4556110081.8947.6007510093.3550.2622410106.0952.67412
10115.5454.6257810134.0857.3443410144.8458.78128
#Mann= 3 , 0 , 0
9855.156   0.055       09855.156   0.055       010144.84   0.055       0
#XS Ineff= 2 , 0
       0                               0
Bank Sta=9855.156,10144.84
Exp/Cntr=0.3,0.1

Type RM Length L Ch R = 1 , 11571.1,89.136700,89.136700,89.136700
XS GIS Cut Line= 6
913557.631423417845826.902151025913610.185379382845894.185169016
913644.184795074 845941.77262117913645.354064281845943.395214626
913676.851099812845987.178523586 913733.44037743846057.059176844
#Sta/Elev= 30
 9855.14 65.3037 9867.1162.573879878.104  58.6119883.35556.089279890.79353.07841
  9899.650.475969903.48249.549489916.17145.16582 9928.8643.032869941.51641.19302
9948.79739.652759953.806 38.80149966.09637.485889978.38635.36401  9983.235.44491
9990.676 35.888210002.9836.11219 10015.336.1425910027.6136.8168310034.6437.32592
10039.9337.9107210054.9440.42481   1006541.9241610077.8743.4081210099.6644.43913
 10103.644.4015310116.4745.2564510129.3446.9372510131.4447.0202910144.8648.39801
#Mann= 3 , 0 , 0
 9855.14    0.04       0 9855.14    0.04       010144.86    0.04       0
#XS Ineff= 2 , 0
       0                               0
Bank Sta=9855.14,10144.86
Exp/Cntr=0.3,0.1

Type RM Length L Ch R = 1 ,11481.97,89.136700,89.136700,89.136700
XS GIS Cut Line= 6
913470.029602944845918.837319912913507.321335828845951.407987032
913539.644235399845976.724438517913639.594332909846044.058562021
913670.291394048846069.452770266913698.768871969846095.734156968
#Sta/Elev= 30
9855.152 76.54539888.30570.507379894.92368.164879901.58365.273959904.66564.24325
 9910.4962.750459914.41861.857989926.70856.805149939.823 48.42839945.72244.95954
9952.17241.642519960.57239.696589964.21538.722649976.25936.164599978.51735.97815
9988.30234.507149996.46234.6401910000.3834.8205310012.4634.5579310014.2534.74084
10024.5236.3638910036.58 39.181810048.6441.6196310067.7244.28873 10083.446.19104
10099.09 48.469410106.0850.1844810114.2652.43793   1012955.4587110144.8358.16606
#Mann= 3 , 0 , 0
9855.152    0.04       09855.152    0.04       010144.83    0.04       0
#XS Ineff= 2 , 0
       0                               0
Bank Sta=9855.152,10144.83
Exp/Cntr=0.3,0.1

Type RM Length L Ch R = 1 ,11392.83,89.136600,89.136600,89.136600
XS GIS Cut Line= 6
913428.347133952845992.425743408913517.725767383846066.656505347
913539.639175152846083.556599373913541.283247399846084.695470062
913592.558442418846125.059376242913652.721741468846175.636489242
#Sta/Elev= 30
9855.14374.656979863.79172.764149874.82470.492929889.78967.053619902.78863.28365
9906.12762.426299915.78759.663059921.77957.636189937.43152.648269941.78551.16701
9954.784 47.09989967.78341.970789980.51335.797629984.98934.688329993.14133.57141
10001.4933.1215210018.4635.1091510031.1837.7781410043.9141.0114410049.9943.43375
10056.64 46.276510066.1649.7255310082.5154.5090910095.5756.8932610097.24 57.1134
10108.6458.0064410112.7858.49879 10121.758.9684510134.7759.4809810144.8560.69789
#Mann= 3 , 0 , 0
9855.143    0.04       09855.143    0.04       010144.85    0.04       0
#XS Ineff= 2 , 0
       0                               0
Bank Sta=9855.143,10144.85
Exp/Cntr=0.3,0.1

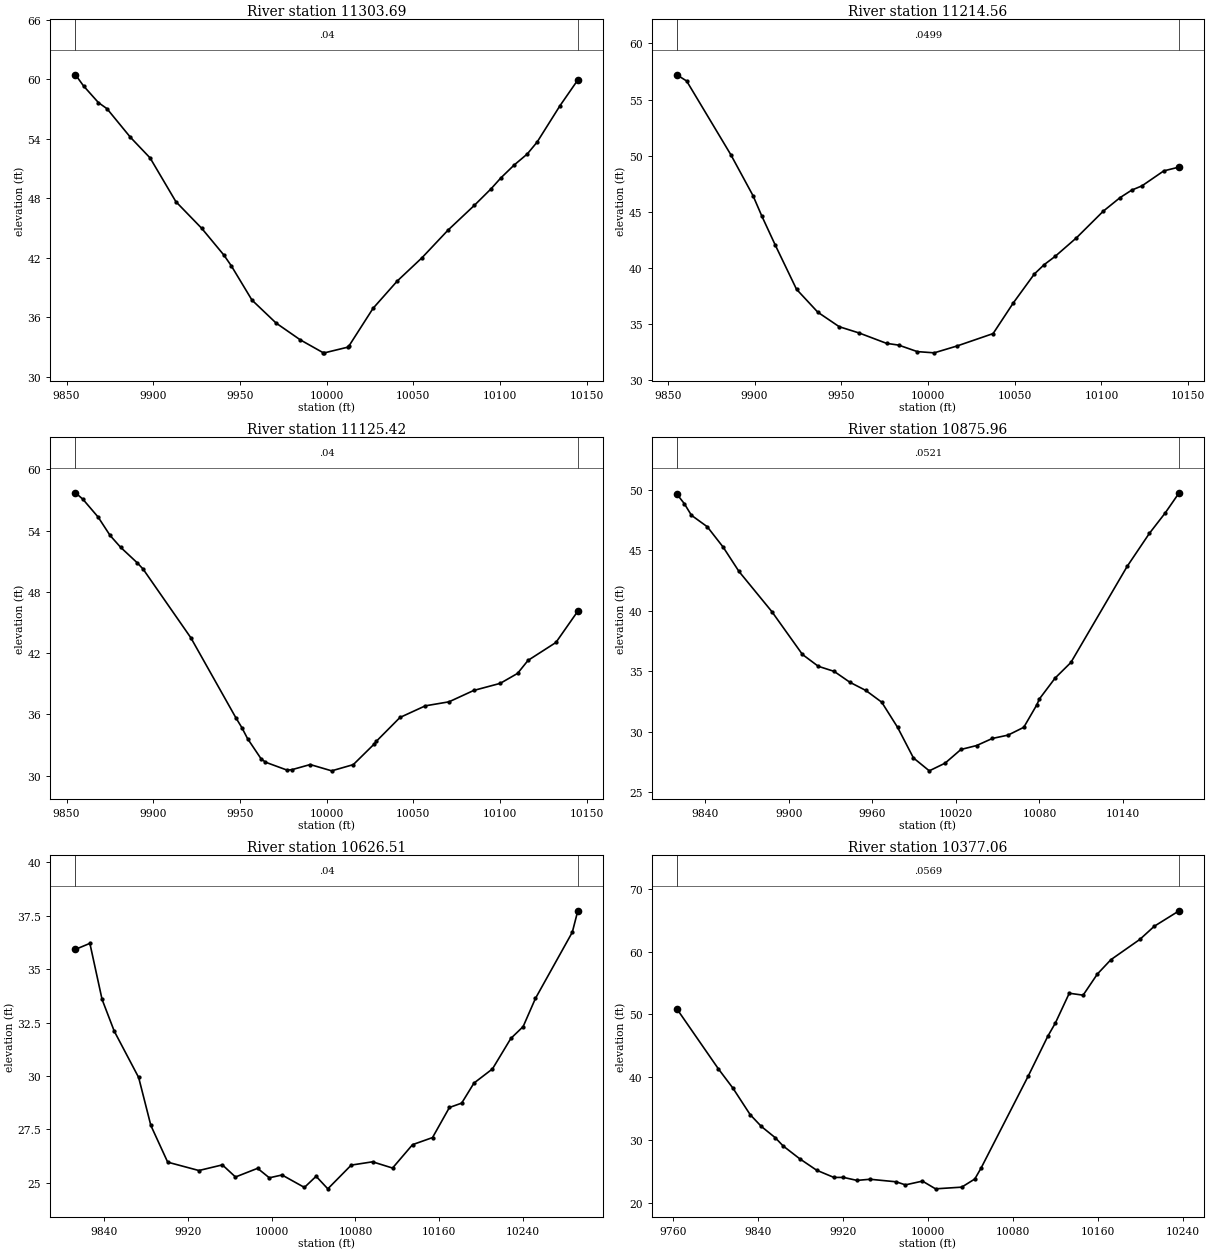
Type RM Length L Ch R = 1 ,11303.69,89.136700,89.136700,89.136700
XS GIS Cut Line= 6
913371.537685941846046.103458102913438.179566128846106.485595356
913475.736322823846145.180010385913477.100523254846146.642527798
913514.950796358846185.058234153913582.691434842846244.187338054
#Sta/Elev= 29
9855.14860.47315 9859.8259.345029868.39857.660439873.314 57.05029886.80854.16638
9898.18452.075599913.07747.655249927.97144.965669940.78642.257149945.07641.16722
9956.942 37.72169970.87835.398049984.81333.705859997.94332.413119998.74932.39588
10012.2632.9712310012.7333.0513810026.77 36.891210040.7539.6525810054.9341.98741
10070.0544.7956210085.2547.2984410094.8248.9590210100.4650.0578410108.0951.35232
10115.6752.4707410121.3653.6723410134.6457.3683410144.85 59.9494
#Mann= 3 , 0 , 0
9855.148    0.04       09855.148    0.04       010144.85    0.04       0
#XS Ineff= 2 , 0
       0                               0
Bank Sta=9855.148,10144.85
Exp/Cntr=0.3,0.1

Type RM Length L Ch R = 1 ,11214.56,89.136700,89.136700,89.136700
XS GIS Cut Line= 6
913300.559945983846134.532238839913375.954011198846191.997969606
913400.423542746 846206.05498144913436.401054287846219.433129422
913458.511079122 846230.85250605913542.032104794846291.597319266
#Sta/Elev= 27
9855.18357.208139860.84756.653819886.36450.067819899.122 46.42519904.24644.59026
 9911.8842.040869924.20838.07518 9936.5236.025199948.83134.736029960.43834.16949
9976.10733.251629983.13133.093689993.85132.5146310003.5832.4052110016.62 33.0097
10037.5534.12241 10049.3 36.880110061.3239.43466   1006740.2697510073.3441.01172
10085.6142.6638210101.0545.0369110110.7946.2533610117.5146.9223610123.3847.29841
10135.9748.6352710144.8348.97582
#Mann= 3 , 0 , 0
9855.183  0.0499       09855.183  0.0499       010144.83  0.0499       0
#XS Ineff= 2 , 0
       0                               0
Bank Sta=9855.183,10144.83
Exp/Cntr=0.3,0.1

Type RM Length L Ch R = 1 ,11125.42,249.454300,249.454300,249.454300
XS GIS Cut Line= 6
913264.938603471846182.282979443913339.933555196846247.270006539
913356.860137215846266.555687775913385.668643891846305.661825771
913407.344433022846328.709422414913472.203884281846382.858340988
#Sta/Elev= 29
9855.16257.69946 9859.4357.069649868.20855.324179875.13853.516599881.17552.36384
9890.84750.830059894.14250.230429921.68343.500919947.70835.647089951.09834.70028
9954.43633.609969962.11731.664359964.72131.314269977.27730.531849980.09730.58758
9990.52731.0826310002.8930.4668810015.3631.0750510027.5533.1148210028.6733.36494
10042.2935.6947210056.8936.8325210070.5637.2265910084.8138.3402710100.0739.03333
10110.0840.0083910116.1441.2855310132.2143.0392510144.8346.10575
#Mann= 3 , 0 , 0
9855.162    0.04       09855.162    0.04       010144.83    0.04       0
#XS Ineff= 2 , 0
       0                               0
Bank Sta=9855.162,10144.83
Exp/Cntr=0.3,0.1

Type RM Length L Ch R = 1 ,10875.96,249.454300,249.454300,249.454300
XS GIS Cut Line= 5
 913075.79339761846402.401457165913233.296869184 846488.12902068
913235.056373709846489.079885458913257.220351071846500.995087462
913393.919866893 846572.26656434
#Sta/Elev= 30
9819.67849.658429825.11348.855249830.15947.904379841.54546.95458 9852.9345.27299
9864.31543.257729887.86639.945269909.85736.397119921.242 35.41859932.62734.99669
9944.01334.091049955.39833.418369966.783 32.45029978.16830.371199989.55427.84241
10000.9426.7739310012.2927.4094310023.6428.5389110034.9428.8666110046.2129.45149
10057.4929.7282510068.7730.3722810078.0932.2221510080.0532.7271710091.3234.44935
 10102.635.7314810142.9843.6730310158.9946.4115510170.2748.0875510180.33 49.7626
#Mann= 3 , 0 , 0
9819.678  0.0521       09819.678  0.0521       010180.33  0.0521       0
#XS Ineff= 2 , 0
       0                               0
Bank Sta=9819.678,10180.33
Exp/Cntr=0.3,0.1

Type RM Length L Ch R = 1 ,10626.51,249.454300,249.454300,249.454300
XS GIS Cut Line= 6
912983.191963833846629.811869882913068.690866273846680.905272207
913146.145564118846720.209197753913147.957201254846721.056529372
913217.466486988846755.763855801913399.484425598846867.703373276
#Sta/Elev= 30
9812.54135.927299826.29736.207849837.94733.583269849.59632.093769872.89529.92643
9884.54527.678099900.63225.959869930.43225.56835 9952.8625.83288 9965.3925.26545
9986.502 25.67139997.71525.2268610009.8325.3598210031.2324.77616 10042.425.29795
10053.5824.7104110075.9425.8218810096.3225.9763810115.4125.68411 10134.526.77922
10153.59 27.111310169.71 28.520210181.4528.7255310193.1929.6643610210.8630.32763
10228.4131.7551210240.1532.3089110251.8933.6272510287.1136.7289210292.3837.73419
#Mann= 3 , 0 , 0
9812.541    0.04       09812.541    0.04       010292.38    0.04       0
#XS Ineff= 2 , 0
       0                10088.83       0
Bank Sta=9812.541,10292.38
Exp/Cntr=0.3,0.1

Type RM Length L Ch R = 1 ,10377.06,249.454300,249.454300,249.454300
XS GIS Cut Line= 6
912828.099913511846716.245779142912873.107607247846764.767462966
912907.772142344846805.726076418913040.654314062846984.288773999
913081.780333693847033.419564779913126.861669375847082.171599824
#Sta/Elev= 30
9763.53850.883319802.75741.300849816.39738.243119832.64934.016939843.12532.14865
9856.22530.353929863.607 29.04729879.08727.021899895.16125.180229911.46224.02829
9920.44624.034179933.10823.557579945.45723.738889970.12423.331959978.73222.84308
9994.79123.4438910007.1122.2132610031.7522.4823810044.0823.7810610050.0425.54032
 10094.340.1470710112.7646.5016810119.9648.63189   1013353.3632510146.0453.05454
 10159.556.4280410172.2158.7067710199.4561.9346110213.0764.0317510236.4666.49416
#Mann= 3 , 0 , 0
9763.538  0.0569       09763.538  0.0569       010236.46  0.0569       0
#XS Ineff= 2 , 0
       09934.525                       0
Bank Sta=9763.538,10236.46
Exp/Cntr=0.3,0.1

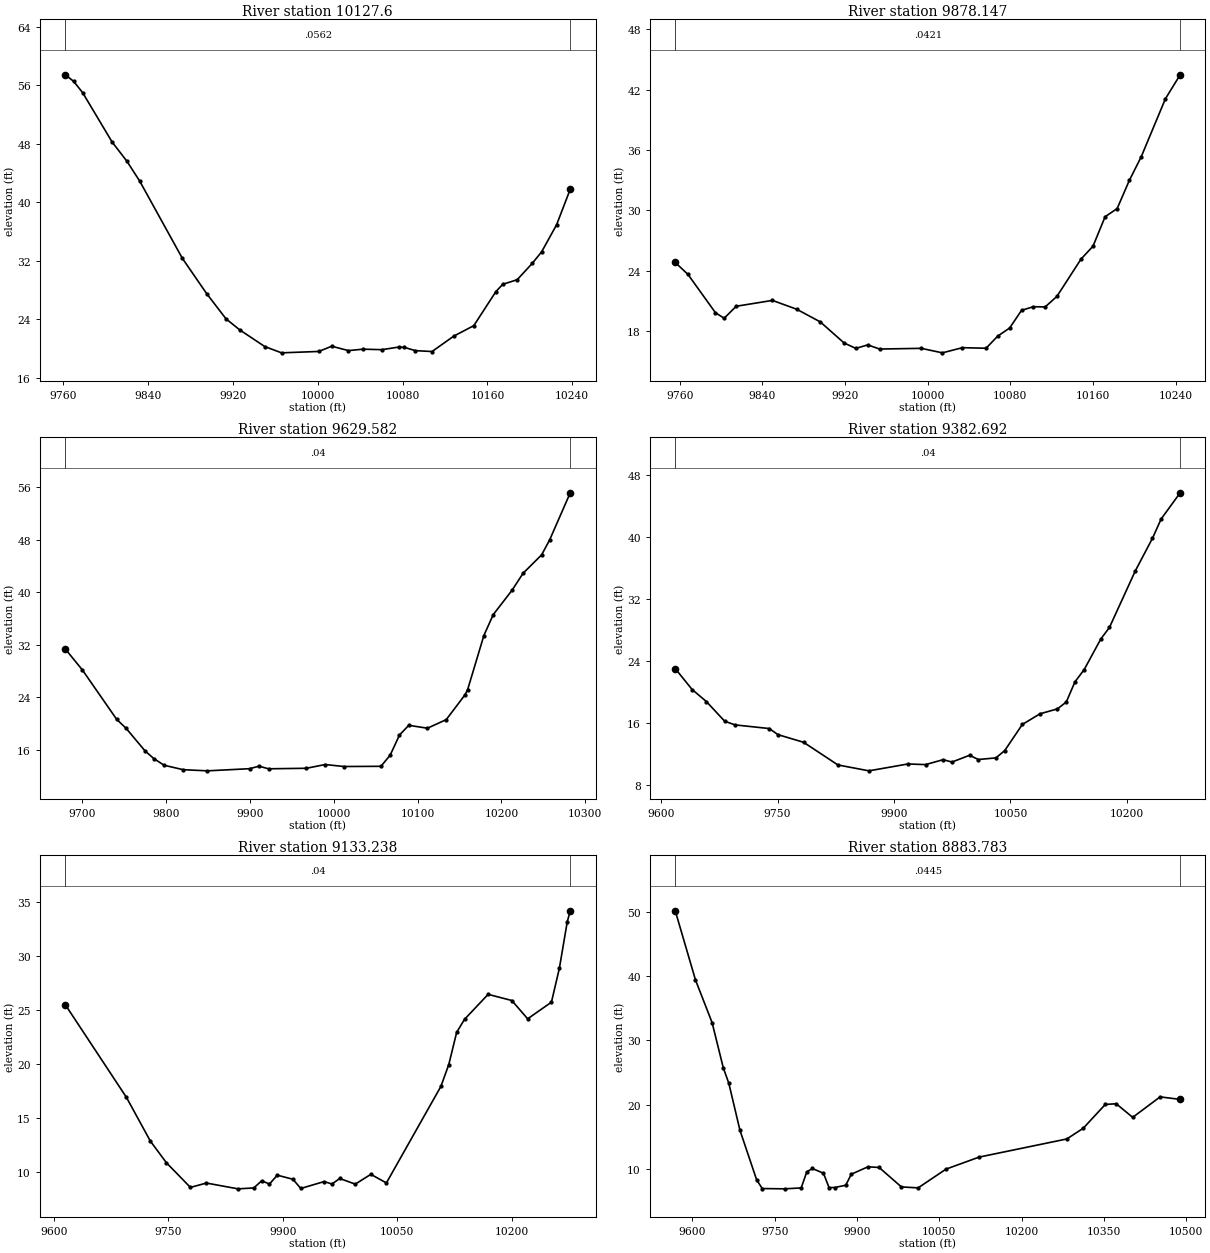
Type RM Length L Ch R = 1 , 10127.6,249.454300,249.454300,249.454300
XS GIS Cut Line= 6
912609.536130736 846853.24534025912658.193409893846903.732774454
 912700.26639633846950.857872172912847.934522835847131.095648169
912888.072532799847174.371678259912924.131436251 847210.33285238
#Sta/Elev= 30
9761.86857.456549769.74256.550559778.193 55.0056 9805.9748.250129819.85845.63355
9831.986 42.90259872.23732.32224 9895.1627.491589913.43724.03375 9926.3622.52614
9949.99120.241699965.77719.38363   1000119.5743410013.0920.2905910028.8719.69014
10042.7219.8855610060.42 19.8178 10076.220.16965 10081.520.1390710091.9819.68473
10107.7619.5639110128.1721.6651610147.1323.1061810167.9727.7685510174.4128.76532
10188.0829.3970510202.2431.63162 10211.133.2103910225.2236.9204310238.1241.79136
#Mann= 3 , 0 , 0
9761.868  0.0562       09761.868  0.0562       010238.12  0.0562       0
#XS Ineff= 2 , 0
       0                               0
Bank Sta=9761.868,10238.12
Exp/Cntr=0.3,0.1

Type RM Length L Ch R = 1 ,9878.147,248.564900,248.564900,248.564900
XS GIS Cut Line= 6
912404.490501206847104.854280166912507.038865496847166.914070283
 912614.74080433847227.609494859912616.487532087847228.583631473
912727.653882444847290.380612615912827.267377386847350.407024395
#Sta/Elev= 30
9755.50824.829129767.79223.645469794.41819.840589802.85819.285379814.54720.47865
9849.61321.06096 9872.9920.18896 9895.99 18.92549918.94716.836599930.42616.29135
9941.90416.642779953.38316.230359993.68516.2986210014.2115.8522610033.6216.36535
 10056.5 16.308210067.9517.5270810079.3918.3220610090.8320.0701710102.2720.43526
10113.7120.4098210125.1521.4629610148.4425.1600510160.1226.4538110171.7929.37113
10183.47 30.184310195.2632.9802410206.8235.3375410230.1741.0831110244.4943.47255
#Mann= 3 , 0 , 0
9755.508  0.0421       09755.508  0.0421       010244.49  0.0421       0
#XS Ineff= 2 , 0
       0                               0
Bank Sta=9755.508,10244.49
Exp/Cntr=0.3,0.1

Type RM Length L Ch R = 1 ,9629.582,246.890000,246.890000,246.890000
XS GIS Cut Line= 6
912210.969973191847295.428464678 912470.44635411847433.462360063
912523.792001005847459.346998365912525.681934722847460.001330486
 912583.97477115847487.667703253912746.923243315847570.486634706
#Sta/Elev= 30
9679.72831.351259700.10828.152169740.92820.639759752.25519.259259774.90915.80305
9785.27814.647349797.56213.630149820.21612.955389849.15512.777359899.50513.10463
9910.83213.487389922.15913.089659967.46613.168169989.81213.7407810012.0413.43663
10056.3113.4678910067.3815.1788810078.4518.2400810089.5219.7188110111.82 19.2785
10134.26 20.589410156.6924.3802310159.7825.1666710179.1333.4083910190.3436.60248
10212.7840.3199410225.9942.9145410248.0645.7140910257.6547.9962610282.2455.18137
#Mann= 3 , 0 , 0
9679.728    0.04       09679.728    0.04       010282.24    0.04       0
#XS Ineff= 2 , 0
       0 9820.59                       0
Bank Sta=9679.728,10282.24
Exp/Cntr=0.3,0.1

Type RM Length L Ch R = 1 ,9382.692,249.454300,249.454300,249.454300
XS GIS Cut Line= 6
 912045.32319399847497.917194853 912253.15660216847595.587366419
912386.458284121847667.037992441 912388.23364826 847667.95890617
912500.505864663847727.721193175912627.148732128847788.555101326
#Sta/Elev= 30
9618.11723.024159639.85920.325159658.28218.769569681.79416.230059695.10515.75441
9739.30215.283879750.351 14.49899783.49813.506039827.69510.579099867.6819.818669
9917.92410.706329940.61610.623769963.30811.260069974.65410.953999997.34511.82831
10008.6711.2813510031.3211.4934810042.65 12.439610065.3115.8098810087.9617.18175
10110.6217.8286210121.9518.7127210133.1721.32692   1014522.8978710166.4526.85891
10177.5528.3425910210.8335.6424510233.0239.8711610244.1142.3509510268.68 45.7441
#Mann= 3 , 0 , 0
9618.117    0.04       09618.117    0.04       010268.68    0.04       0
#XS Ineff= 2 , 0
       0                               0
Bank Sta=9618.117,10268.68
Exp/Cntr=0.3,0.1

Type RM Length L Ch R = 1 ,9133.238,249.454300,249.454300,249.454300
XS GIS Cut Line= 6
911928.729626313847798.904263015912104.464743243847853.971348753
912176.346928255847872.714397247 912240.70833491847887.121803104
912404.012321995847918.882804881912568.764713418 847962.44844925
#Sta/Elev= 30
9615.33625.489189695.26316.923869726.70112.86052 9747.6610.863589779.099 8.57894
 9800.058.9813689841.3878.4457269862.0568.528351 9872.399.186134 9882.658.894815
9892.8979.7105069913.3929.331528 9923.64  8.47969954.2799.1202779964.4558.893115
9974.6319.4036759994.9828.88174810015.369.78799510035.758.99165610107.1217.93093
10117.4319.9502810127.7322.9305510138.0424.1399710168.9626.4538110199.9725.88479
10220.7324.1896510251.8725.7298810262.2528.8641210272.6333.1915510276.5334.19314
#Mann= 3 , 0 , 0
9615.336    0.04       09615.336    0.04       010276.53    0.04       0
#XS Ineff= 2 , 0
       09828.527                       0
Bank Sta=9615.336,10276.53
Exp/Cntr=0.3,0.1

Type RM Length L Ch R = 1 ,8883.783,249.454300,249.454300,249.454300
XS GIS Cut Line= 5
911828.738500077848070.466834697912252.794408944 848143.20290182
 912254.75644069848143.590756747912325.322575333 848156.80792173
912741.517474281848162.619096776
#Sta/Elev= 30
9568.75150.119159605.54239.39693 9635.9832.726979656.27325.729879666.41923.31205
9686.71116.009379717.1498.3083149727.2956.9682059767.8796.9218289798.3177.062542
9808.4639.5538849818.60910.083049838.9019.3441879849.0477.1151619859.1937.129283
9879.4857.4779949889.6319.196616 9920.0710.348499940.36210.239169980.9467.220928
10011.427.07150210062.299.98570810122.48 11.850210282.4914.6715610312.4916.34343
 10352.520.03155 10372.520.14118 10402.518.0254610452.5121.2088610489.0320.81573
#Mann= 3 , 0 , 0
9568.751  0.0445       09568.751  0.0445       010489.03  0.0445       0
#XS Ineff= 2 , 0
       09927.136        10073.17       0
Bank Sta=9568.751,10489.03
Exp/Cntr=0.3,0.1

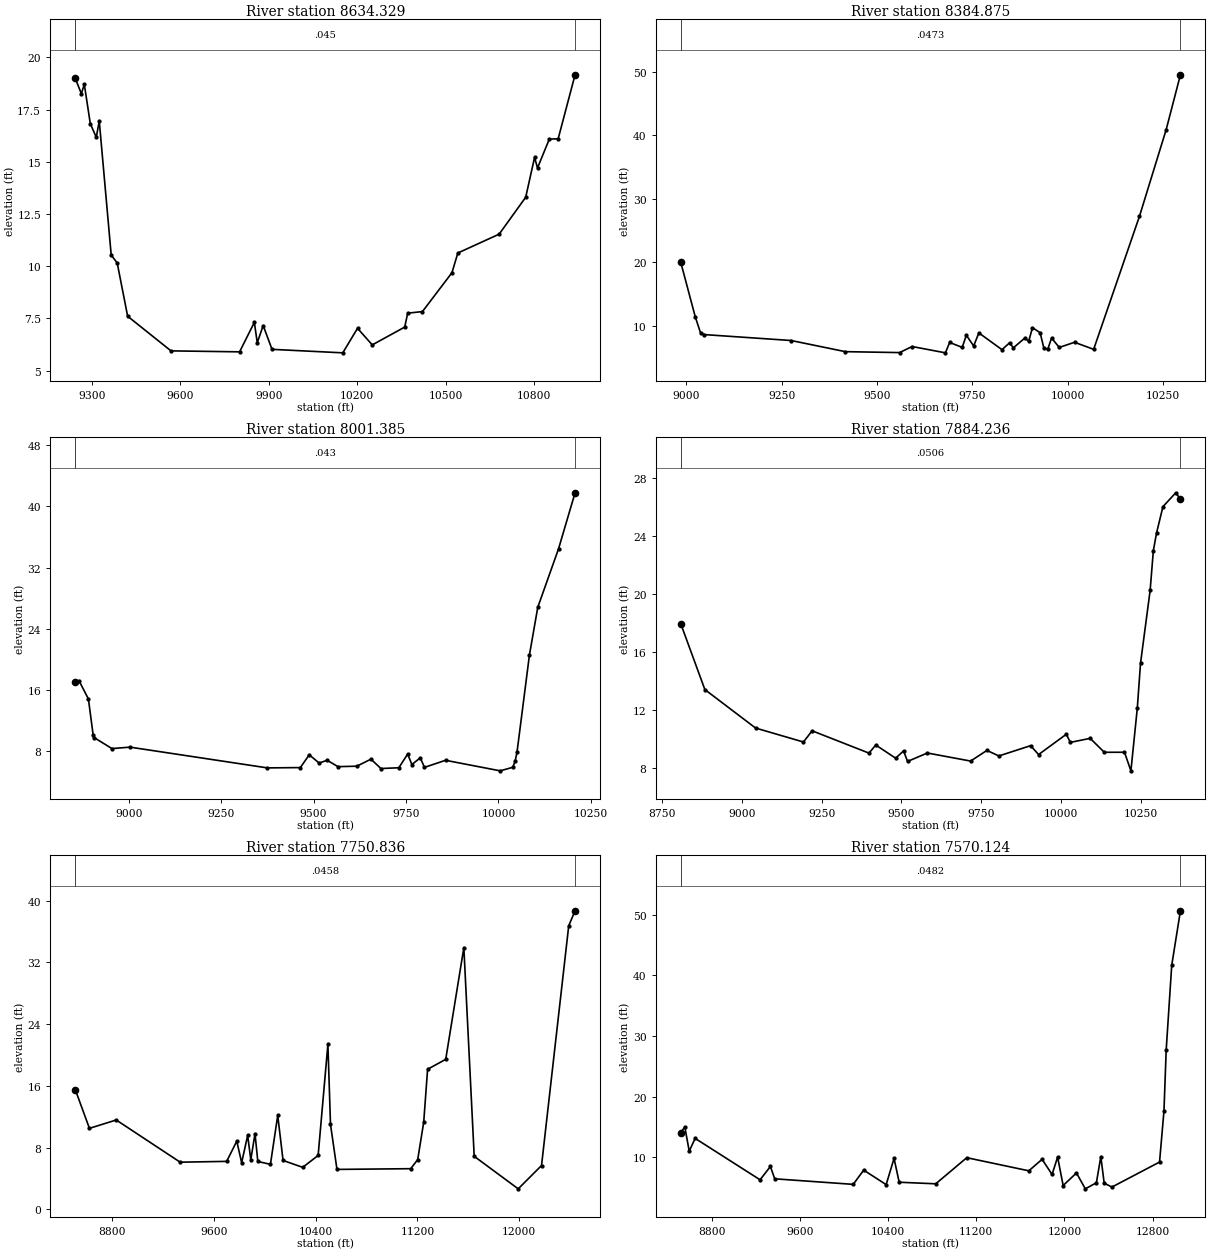
Type RM Length L Ch R = 1 ,8634.329,249.454300,249.454300,249.454300
XS GIS Cut Line= 6
911484.951597234848305.004241045912007.851817307848394.610623266
912173.781116841848395.291040006912275.363215944848387.903211435
912439.508899148848386.108514306913172.286893474848429.771683976
#Sta/Elev= 30
9243.17518.991099263.51618.265099273.66218.708549293.953 16.82799314.24516.17316
9324.39116.948139364.97410.529349385.26510.157739420.7687.6032769567.8895.944812
9800.8555.8980329850.8737.3077169860.8766.333485 9880.887.1594889910.8866.017748
 10151.25.85031310201.217.02620810251.296.23111110361.487.084816 10371.57.750466
10421.597.82667610521.779.687874 10541.810.6328510682.0511.5347810772.2113.30271
10802.2615.2102310812.2814.7054110852.35  16.088 10882.416.1030810939.7919.16879
#Mann= 3 , 0 , 0
9243.175   0.045       09243.175   0.045       010939.79   0.045       0
#XS Ineff= 2 , 0
       09926.329        10167.83       0
Bank Sta=9243.175,10939.79
Exp/Cntr=0.3,0.1

Type RM Length L Ch R = 1 ,8384.875,383.489600,383.489600,383.489600
XS GIS Cut Line= 6
911310.157594923848323.961637414912030.984316567848643.162891528
912190.952778556848644.556730721912371.692282226848633.083498543
912456.973946596848634.467233004912552.267566842848641.049896699
#Sta/Elev= 30
 8985.3620.031229023.46611.41138 9037.328.8743939045.3398.6019399275.0087.660796
9417.184 5.90219 9559.365.756411 9592.176.7150019679.4495.717072  9690.6 7.35444
 9723.416.5760539734.3468.4889939753.5416.8045349767.1568.8598689827.7496.219014
9847.7617.3025939857.767 6.510199887.7748.0563469897.7767.5367919907.7789.692649
9927.7828.8925019937.7956.4186399947.8246.2839249957.8538.0595169977.9116.567195
10018.037.38083310068.156.26897910188.1927.2312810258.3340.9227310295.6949.56646
#Mann= 3 , 0 , 0
 8985.36  0.0473       0 8985.36  0.0473       010295.69  0.0473       0
#XS Ineff= 2 , 0
       09893.269                       0
Bank Sta=8985.36,10295.69
Exp/Cntr=0.3,0.1

Type RM Length L Ch R = 1 ,8001.385,117.149100,117.149100,117.149100
XS GIS Cut Line= 4
911267.223998122848343.449145357911955.413755331848885.981905475
912234.185817847849037.011742867912374.822402705849108.845828679
#Sta/Elev= 30
8855.74917.043268865.65117.231698891.11914.830958903.85310.148958906.7129.782755
8954.788 8.349639003.6278.5387749375.0025.8264089464.1395.8665989488.2027.532226
9515.0746.4632469536.6596.8218759566.0095.9888729616.9446.0483049655.1466.969086
9682.0325.7431659730.4895.8438849754.3517.6352789765.7246.2683099788.4717.137932
9799.8445.8923479856.711 6.8193610004.56 5.4412910038.685.90573710044.916.687824
10050.047.87194610083.7320.6062110106.1926.8191410162.33 34.461210207.0541.79042
#Mann= 3 , 0 , 0
8855.749   0.043       08855.749   0.043       010207.05   0.043       0
#XS Ineff= 2 , 0
       09774.982                       0
Bank Sta=8855.749,10207.05
Exp/Cntr=0.3,0.1

Type RM Length L Ch R = 1 ,7884.236,133.400500,133.400500,133.400500
XS GIS Cut Line= 5
911247.954563636848354.990250367911373.394040271848517.689188074
911528.217206136 848661.33311984912296.516023666849231.668589375
912489.517715255849251.463634682
#Sta/Elev= 30
8807.55317.955888883.32713.402259042.46710.744749192.5199.7807099219.80110.55402
9398.1129.014721 9419.459.573005 9481.728.6646889506.629 9.165749519.0838.439986
9581.3549.0208749716.8758.4650169768.1669.2015049805.5298.8179959905.1629.529028
 9930.078.91437110017.2510.31731 10029.79.75486710091.9710.03389 10136.3 9.07123
10199.629.07314810219.737.79041710239.8312.1293210249.8815.2204410280.0420.24791
10290.0922.9885810300.1524.2129210320.25 26.032710360.4626.9877510375.0626.54918
#Mann= 3 , 0 , 0
8807.553  0.0506       08807.553  0.0506       010375.06  0.0506       0
#XS Ineff= 2 , 0
       09766.495        10067.69       0
Bank Sta=8807.553,10375.06
Exp/Cntr=0.3,0.1

Type RM Length L Ch R = 1 ,7750.836,180.711500,180.711500,180.711500
XS GIS Cut Line= 4
910951.362429742848333.924375147911882.676129373849143.723916904
912559.978680698849459.675628509914474.041180711849090.752017457
#Sta/Elev= 30
8509.094 15.50178619.92810.507138830.77711.589679333.7036.1236639699.466 6.22851
 9778.918.8486729817.2256.0604229864.5349.5844599889.2556.4566059922.3599.815419
9944.428  6.214410043.745.84635310101.0812.1811310143.056.34882410297.535.455802
10418.916.99627210495.7321.39018 10516.111.0233410567.025.18820611147.515.281646
 11202.2 6.4704711249.3511.30719 11279.918.1599811422.4819.4461211565.0533.91656
11646.536.88327511992.782.671367 12176.15.69203912389.9636.7420412439.9138.68995
#Mann= 3 , 0 , 0
8509.094  0.0458       08509.094  0.0458       012439.91  0.0458       0
#XS Ineff= 2 , 0
       09774.767        10078.76       0
Bank Sta=8509.094,12439.91
Exp/Cntr=0.3,0.1

Type RM Length L Ch R = 1 ,7570.124,564.757900,564.757900,564.757900
XS GIS Cut Line= 6
910917.239143878848458.136933372911850.711034884849288.677601971
911926.501721898849344.186541784912180.708910151849501.466837902
912447.131458434849681.029795211915003.555069569849932.765906305
#Sta/Elev= 30
8520.52714.027028557.685  14.9828597.84110.977848651.38113.088069240.328 6.25018
9334.0258.4478479373.3176.41364310085.175.49750510180.157.84629210383.945.454484
10455.519.77992210502.155.84794410833.755.589634 11115.19.90006211677.817.734275
11798.399.63319111888.837.12571911939.0710.0078611989.315.30381312109.897.382152
12190.284.75833412290.765.76073412330.9510.0672312361.485.69485512431.445.050702
12863.52 9.1773612903.7117.6302712923.8127.6706112974.0541.6631813052.9850.65597
#Mann= 3 , 0 , 0
8520.527  0.0482       08520.527  0.0482       013052.98  0.0482       0
#XS Ineff= 2 , 0
       09791.501         10119.7       0
Bank Sta=8520.527,13052.98
Exp/Cntr=0.3,0.1

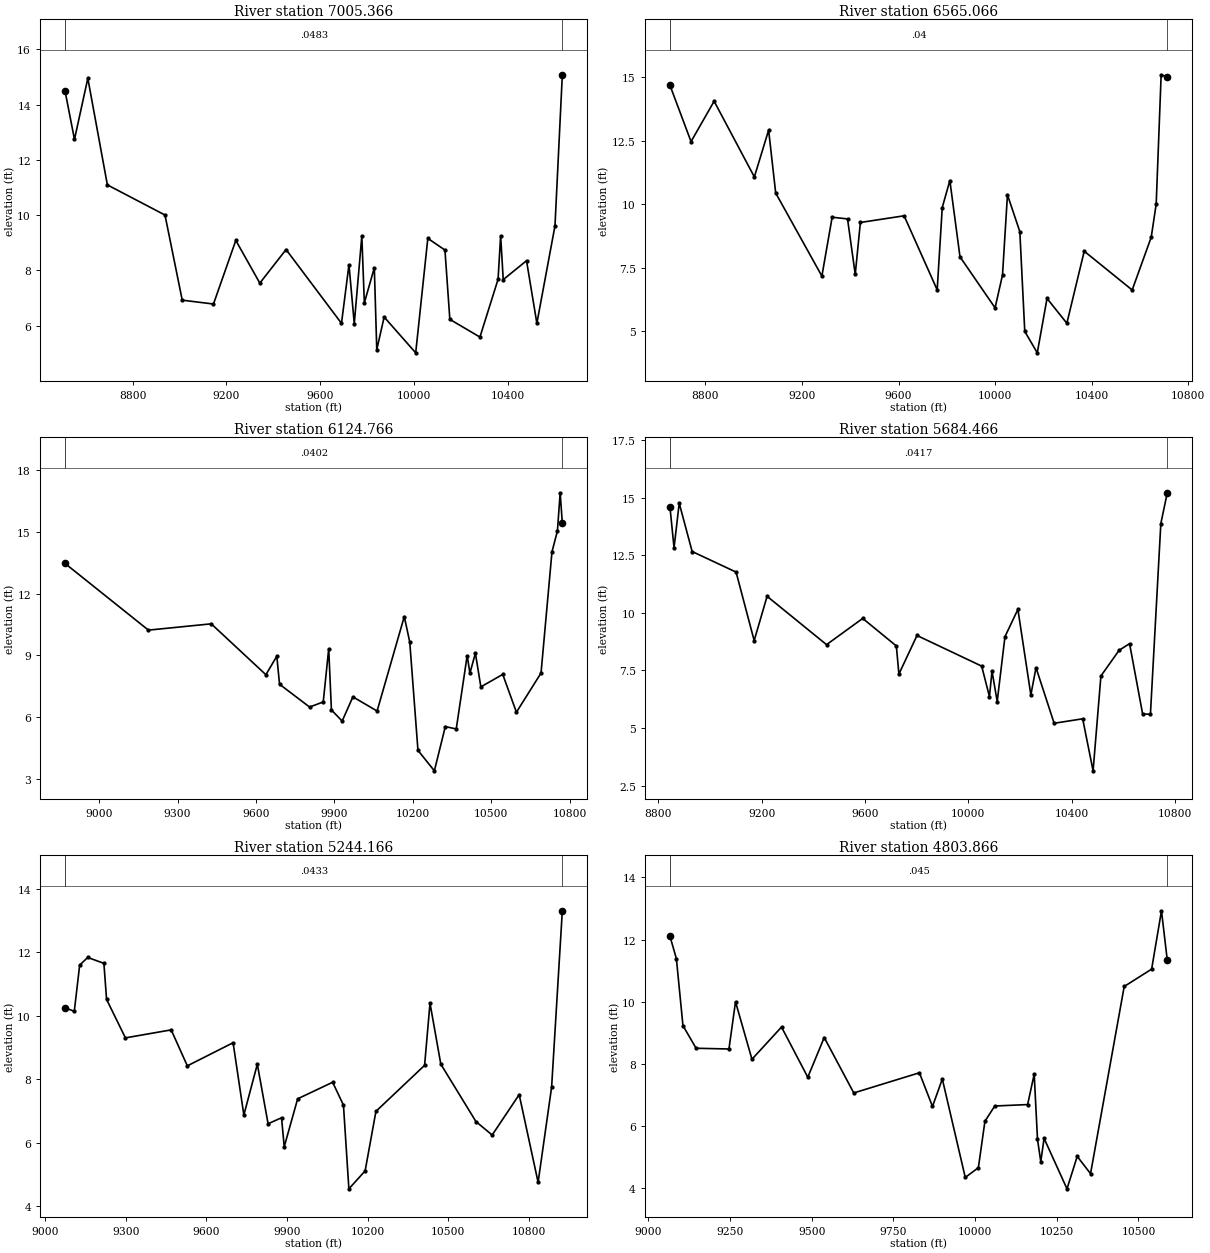
Type RM Length L Ch R = 1 ,7005.366,440.300000,440.300000,440.300000
XS GIS Cut Line= 6
910912.937757598848503.173774106911542.479277445849474.970074836
911598.057138425849607.387652108 911692.40335449849937.858418252
911729.851259601850039.614933802911886.219152979850373.346050872
#Sta/Elev= 30
8511.24914.510428551.82712.742668608.74514.957468692.14911.094858938.07210.00193
9011.6426.9183049144.918  6.77839240.2379.0832219342.7097.5356969454.7068.752312
9691.1786.0787699723.1338.2017459745.7366.0678789777.9859.2445559788.734 6.82075
9831.2778.0908239841.7685.1262829873.2416.30718310007.885.00988310059.589.156809
10132.688.73403210153.58 6.2219710281.985.58118610359.297.67274710370.339.251335
10381.377.66163810480.76 8.3477210524.936.08069410602.249.61215910633.5415.08405
#Mann= 3 , 0 , 0
8511.249  0.0483       08511.249  0.0483       010633.54  0.0483       0
#XS Ineff= 2 , 0
       09774.995        10098.23       0
Bank Sta=8511.249,10633.54
Exp/Cntr=0.3,0.1

Type RM Length L Ch R = 1 ,6565.066,440.300000,440.300000,440.300000
XS GIS Cut Line= 6
910776.595840632 848592.73500244911135.213580624849589.450623679
911202.227710157849800.375656611911217.279588759 849865.93729513
911269.373063824850100.221905397911378.640039336 850559.70601452
#Sta/Elev= 30
 8653.1514.679918740.57812.463658836.22614.050949002.88611.074089061.96112.91375
9091.28810.441099282.5847.1755159325.095 9.49121 9388.869.4238929420.7437.243779
9441.998 9.283859623.1749.5468289760.2116.6347279781.1969.8721329812.67410.93356
9854.6447.93350710000.045.92782710030.77 7.2206310051.2610.3717310102.488.925998
10122.975.00154510174.794.15898110215.176.29723410297.315.32186910369.26 8.15495
 10567.96.62881310646.798.70538710667.3510.0066310687.9115.09082 10713.315.00312
#Mann= 3 , 0 , 0
 8653.15    0.04       0 8653.15    0.04       0 10713.3    0.04       0
#XS Ineff= 2 , 0
       09893.114        10078.62       0
Bank Sta=8653.15,10713.3
Exp/Cntr=0.3,0.1

Type RM Length L Ch R = 1 ,6124.766,440.300000,440.300000,440.300000
XS GIS Cut Line= 6
910462.395428581848849.511976646910756.074327044849819.859440945
910782.395819216849932.436807387910782.898404792849934.372629634
910805.177342414 850027.29128781911003.215120694850672.877426017
#Sta/Elev= 30
8869.57113.468739188.74410.231079429.047 10.53639638.0068.0679029679.7988.964878
9690.2467.6055819805.1746.4983449857.4136.7473579878.3099.3270029888.6666.356914
9929.7445.8185139970.8236.99403210063.356.30521710167.3810.8891810188.299.650784
10219.674.39803510282.433.40355910324.275.55092810366.115.43514210407.958.997357
10418.418.14117810439.339.11233510460.257.47685910543.938.08364110596.236.247855
10690.378.14685610732.2114.0277710753.1315.0478310763.5916.8951810771.8315.42414
#Mann= 3 , 0 , 0
8869.571  0.0402       08869.571  0.0402       010771.83  0.0402       0
#XS Ineff= 2 , 0
       09873.551        10160.29       0
Bank Sta=8869.571,10771.83
Exp/Cntr=0.3,0.1

Type RM Length L Ch R = 1 ,5684.466,440.300000,440.300000,440.300000
XS GIS Cut Line= 6
910355.259789429848849.082984245910341.382420345849816.541583568
910347.031604673849915.723073749910352.664825146 850091.37332675
910336.667620061850405.394996346910289.883179279850769.724367762
#Sta/Elev= 30
8845.22814.606468861.14612.821298881.148 14.75988931.15312.662499101.16911.76967
9171.1768.7974799221.18110.718959451.2038.6208839591.216 9.759659721.2318.564136
9731.2327.3453599801.2439.01870310051.487.68972510081.496.367623 10091.57.471681
10111.536.15393310141.578.96741510191.64 10.151810241.716.44024410261.737.622268
10331.825.20979710442.235.40430910482.563.146148 10512.87.26180410583.388.378554
10623.718.66432310674.125.62142710704.36   5.59510744.6913.8756610769.6215.21081
#Mann= 3 , 0 , 0
8845.228  0.0417       08845.228  0.0417       010769.62  0.0417       0
#XS Ineff= 2 , 0
       0 9853.92        10201.28       0
Bank Sta=8845.228,10769.62
Exp/Cntr=0.3,0.1

Type RM Length L Ch R = 1 ,5244.166,440.300000,440.300000,440.300000
XS GIS Cut Line= 6
 909947.91749144849110.403587418909907.129462897849848.682409904
909911.500802469849985.112592229909907.675661418850106.330316851
909894.044816306850217.679414333909815.282229366850954.589351973
#Sta/Elev= 30
9074.06110.261999108.70710.143749128.73611.602279158.77911.843869218.86611.65827
 9228.8810.521079298.9819.3083129469.2279.5605549529.3138.4264079699.5729.155255
9739.647  6.87659789.7428.4785229829.7956.600409 9879.826.7906969889.825 5.87668
9939.8517.38747910069.94 7.9091910110.237.18799510130.384.54937410190.815.114213
10231.056.99199610412.118.44248910432.2210.4023110472.458.47977910603.186.670153
10663.516.24556510764.077.51886710834.474.75459310884.757.75841510924.5613.31525
#Mann= 3 , 0 , 0
9074.061  0.0433       09074.061  0.0433       010924.56  0.0433       0
#XS Ineff= 2 , 0
       09837.814        10199.13       0
Bank Sta=9074.061,10924.56
Exp/Cntr=0.3,0.1

Type RM Length L Ch R = 1 ,4803.866,504.077500,504.077500,504.077500
XS GIS Cut Line= 6
909544.074048372849115.343985116 909472.09334035849805.602587078
909463.132251746849939.982034378909492.394013775 850249.78085761
909527.822308794850440.798452741909577.707695176850622.119330376
#Sta/Elev= 30
9065.92912.110389085.693 11.38699105.8039.2323429146.023 8.504479246.5748.481395
9266.6859.999977 9316.968.1505929407.4569.1872869487.8977.5727019538.172 8.85083
9628.6537.0669349829.4827.7161329869.5716.6320139899.6437.5147719969.8684.348868
   100104.66220510030.076.15650910060.186.64748110160.746.69283210180.887.672376
10190.955.57288910201.024.85684510211.125.60631510281.233.98226610312.555.026785
10353.314.47057710456.3610.49255 10540.311.0504110570.4512.92748 10588.211.33569
#Mann= 3 , 0 , 0
9065.929   0.045       09065.929   0.045       0 10588.2   0.045       0
#XS Ineff= 2 , 0
       09864.324        10173.32       0
Bank Sta=9065.929,10588.2
Exp/Cntr=0.3,0.1

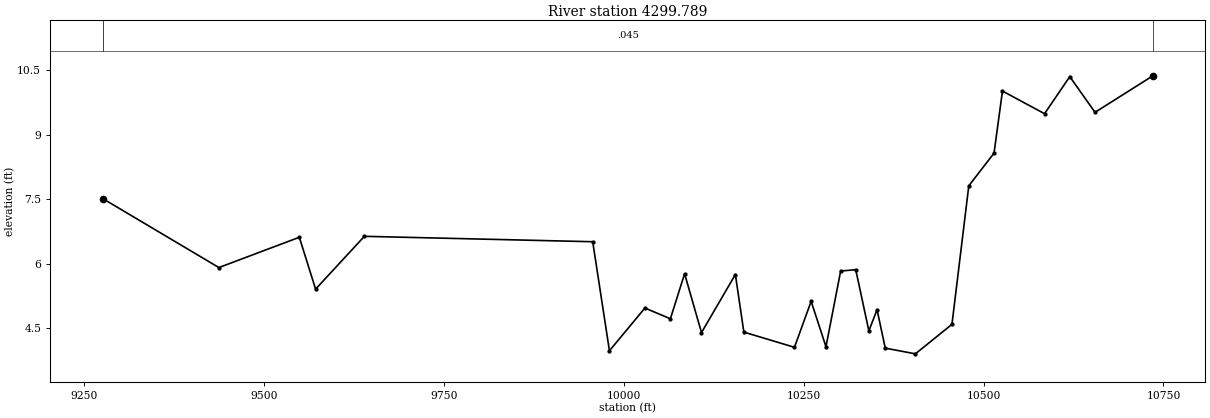
Type RM Length L Ch R = 1 ,4299.789,0.000000,0.000000,0.000000
XS GIS Cut Line= 6
908679.865210497849453.488784305908946.534271099849963.830736378
908984.086737748850031.201359024909133.526929425850279.039655036
 909219.53757334850432.555328634909395.997919338850723.786514156
#Sta/Elev= 30
 9276.447.5150289437.6675.9111649549.4046.6161199572.0095.4089439639.8236.638537
9957.0316.5123989980.2573.97376510029.544.96866210064.934.71903810084.685.767012
10108.164.39699510155.235.749497   101674.40816910237.324.054731 10260.5 5.12526
10281.094.067891 10301.55.83009410322.455.86177310340.694.43721810352.074.929957
10363.454.03532910405.353.90233110456.134.58904410479.527.81456410514.598.574833
10526.2910.0208310584.759.49325910619.8310.35625 10654.99.52514910735.3310.37614
#Mann= 3 , 0 , 0
 9276.44   0.045       0 9276.44   0.045       010735.33   0.045       0
#XS Ineff= 2 , 0
       0 9884.77        10158.92       0
Bank Sta=9276.44,10735.33
Exp/Cntr=0.3,0.1